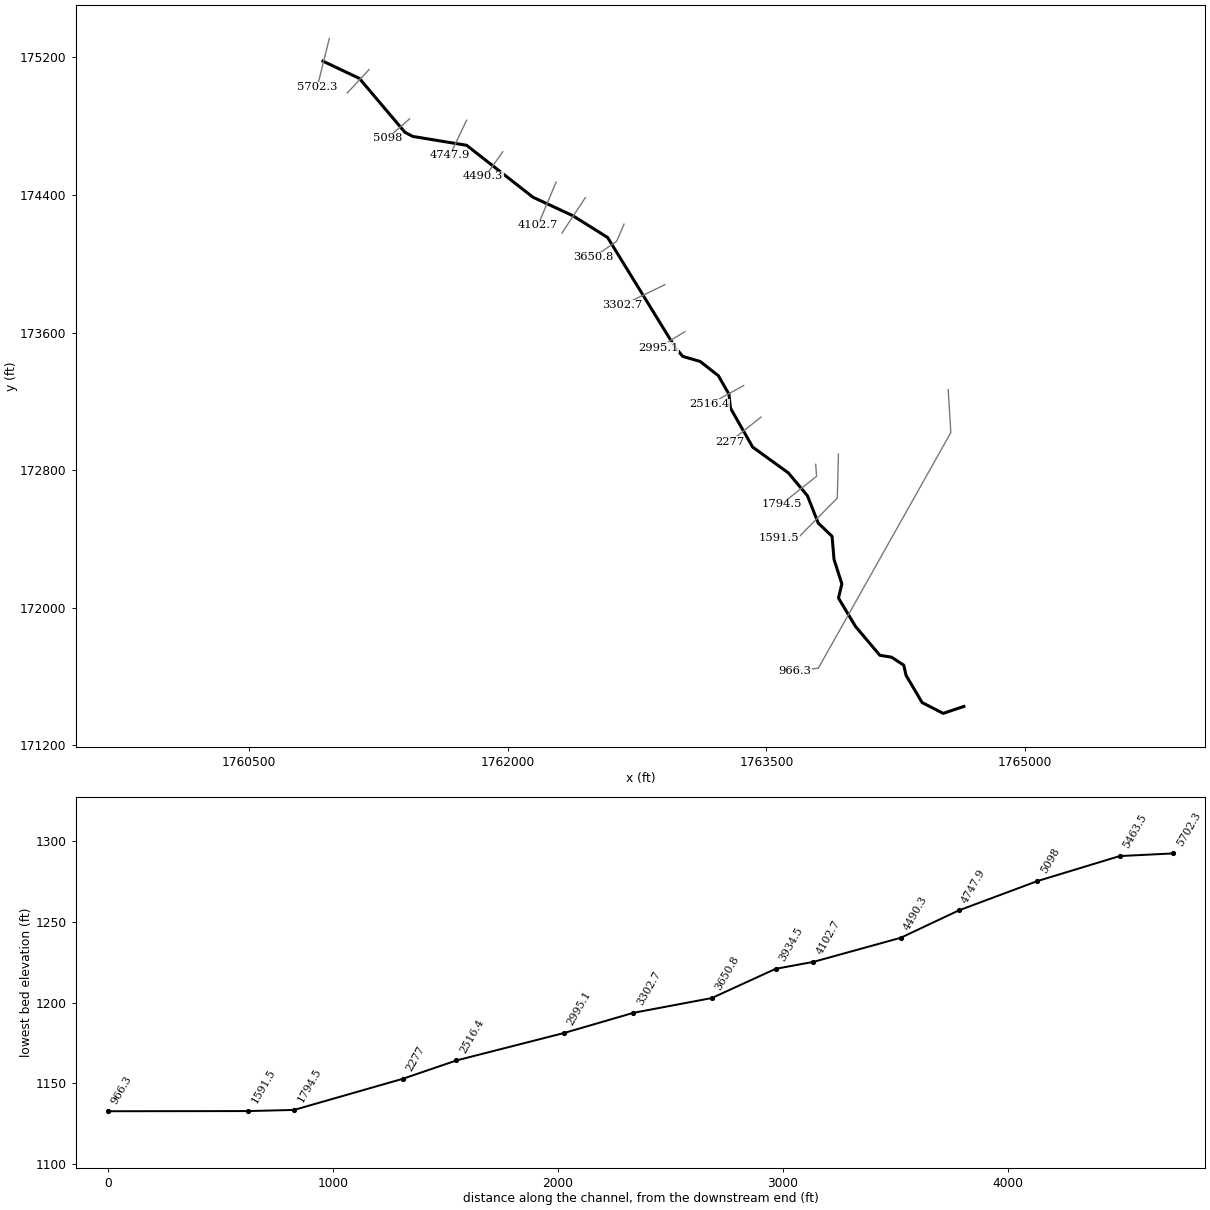
--- Lower Hensley Creek.prj (project) ---

Proj Title=Lower Hensley Creek
Current Plan=p01
Default Exp/Contr=0,0
English Units
Geom File=g01
Flow File=f01
Plan File=p01
BEGIN DESCRIPTION:
END DESCRIPTION:
DSS Export Rating Curves= 0
DSS Export Rating Curve Sorted= 0
DSS Export Volume Flow Curves= 0
DXF OffsetX= 0
DXF OffsetY= 0
DXF ScaleX= 0
DXF ScaleY= 0

--- Lower Hensley Creek.p01 (plan) ---

Plan Title=Floodplain
Program Version=4.00
Geom File=g01
Flow File=f01
K Sum by GR=0
Std Step Tol=0.01
Critical Tol=0.01
Num of Std Step Trials=20
Max Error Tol=0.3
Flow Tol Ratio=0.001
Split Flow NTrial=30
Split Flow Tol=0.02
Split Flow Ratio=0.02
Log Output Level=0
Friction Slope Method=1
Unsteady Friction Slope Method=2
Unsteady Bridges Friction Slope Method=1
Global Log Level=0
CheckData=False
Run HTab=0
Run UNet=0
Run PostProcess=0
UNET Theta=0
UNET Theta Warmup=0
UNET ZTol=0
UNET ZSATol=0
UNET MxIter=0
UNET MaxInSteps=0
UNET DtIC=0
UNET DtMin=0
UNET MaxCRTS=0
UNET WFStab=0
UNET SFStab=0
UNET WFX=0
UNET SFX=0
UNET DSS MLevel=0
UNET DZMax Abort=0
UNET Convert EG Bridges=0
UNET Use Existing IB Tables=0
UNET Froude Limit=0
UNET Froude Power=0
Write IC File=0
Echo Input=False
Echo Output=False
Write Detailed=0

--- Lower Hensley Creek.f01 (steady flow) ---

Flow Title=NFF Regression Equation
Program Version=4.00
Number of Profiles=1
Profile Names=P100yr
River Rch & RM=Lower Hensley...,Main      ,5702.3
568.9144
River Rch & RM=Lower Hensley...,Main      ,5098
585.9959
River Rch & RM=Lower Hensley...,Main      ,4490.3
644.6392
River Rch & RM=Lower Hensley...,Main      ,3302.7
694.8129
River Rch & RM=Lower Hensley...,Main      ,1794.5
771.8586
Boundary for River Rch & Prof#=Lower Hensley...,Main      ,1
Up Type=0
Dn Type=3
Dn Slope=0.016925

--- Lower Hensley Creek.g01 (geometry) ---

Geom Title=Geometry
Program Version=4.00

River Reach=Lower Hensley...,Main
Reach XY= 30
     1760927.132      175177.677       1761138.9      175077.164
     1761402.944       174764.06     1761448.056      174740.052
     1761760.561       174688.59     1762145.853      174386.494
     1762376.076      174279.605     1762578.343      174152.982
     1762968.808      173516.451     1763014.381      173461.471
      1763116.08      173431.616     1763221.325      173348.845
     1763282.717      173241.407     1763291.488      173160.281
     1763420.338      172933.864     1763627.109      172784.131
     1763737.683      172651.597      1763800.72      172492.085
      1763880.75      172415.344     1763892.253      172281.052
     1763937.758      172138.528     1763918.025      172056.305
      1764017.24      171890.763     1764158.115      171723.577
     1764226.085      171712.614     1764296.797      171666.021
     1764309.952      171607.369     1764403.138      171448.954
     1764525.376      171385.916       1764645.5      171426.266

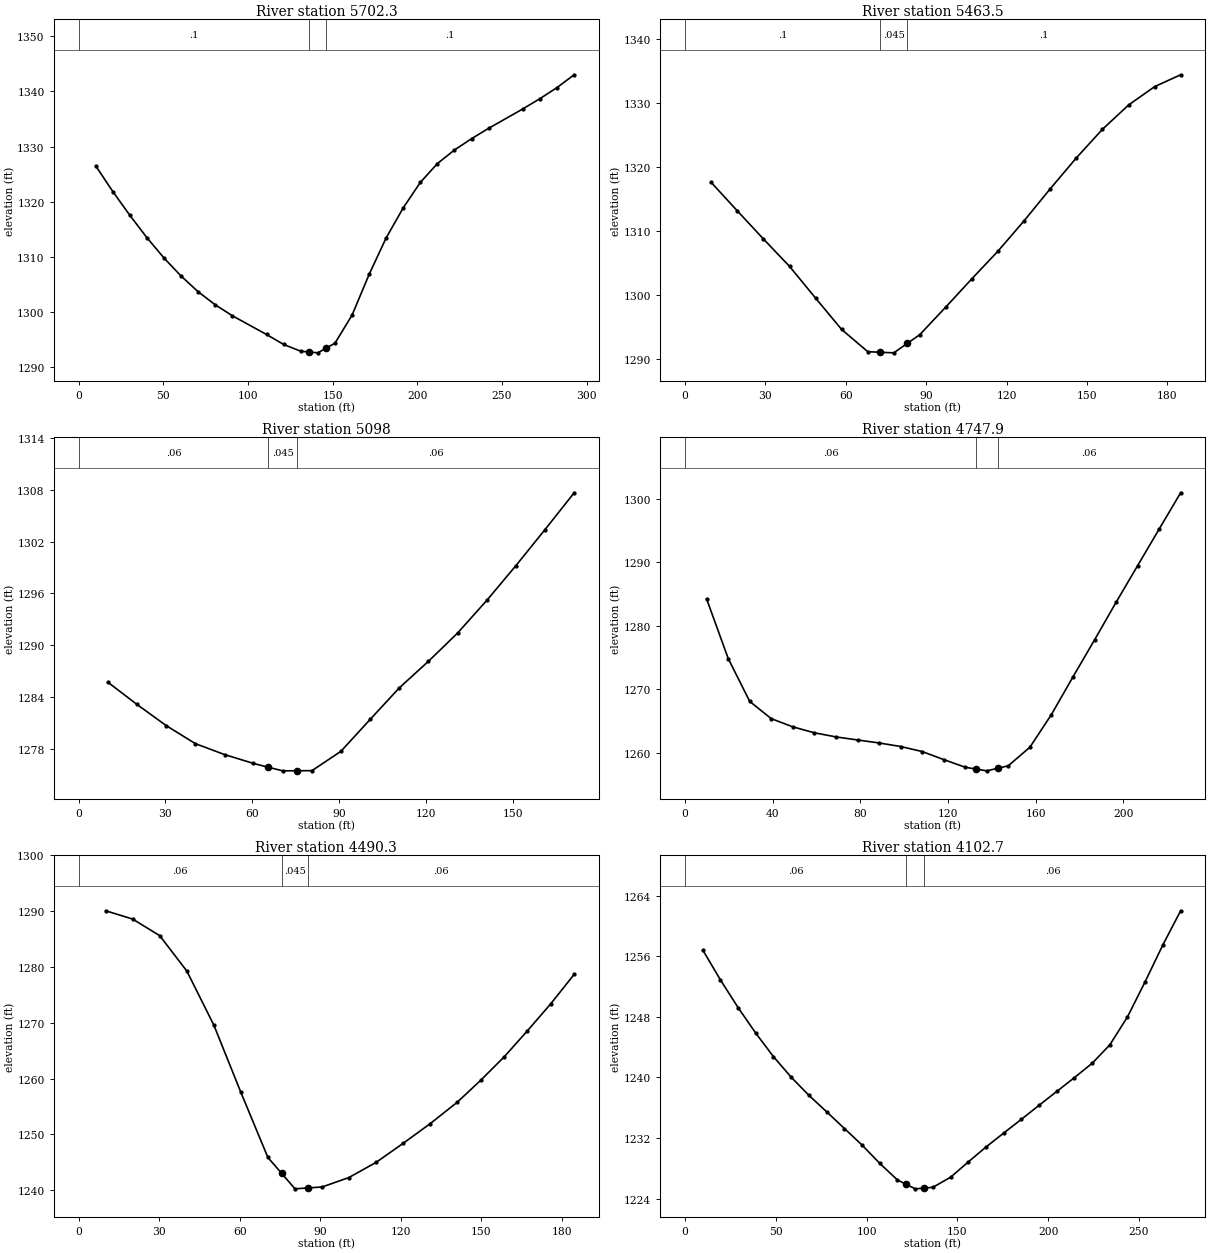
Type RM Length L Ch R = 1 ,5702.3  ,248.9,238.8,228.7
XS GIS Cut Line= 2
     1760964.436      175310.258     1760894.081      175026.186
#Sta/Elev= 29
    10.1  1326.5    20.2 1321.84    30.3 1317.51    40.4 1313.45    50.5 1309.76
    60.5 1306.52    70.6 1303.66    80.7  1301.3    90.8 1299.31     111 1295.91
   121.1  1294.1   131.2 1292.87   136.3 1292.73   141.3 1292.58   146.3 1293.45
   151.4 1294.33   161.5 1299.42   171.6 1306.82   181.6 1313.41   191.7 1318.87
   201.8 1323.49   211.9 1326.92     222 1329.38   232.1 1331.44   242.2 1333.32
   262.4 1336.84   272.5  1338.7   282.6 1340.72   292.7 1343.03
#Mann= 3 , 0 , 0
       0      .1       0   136.3    .045       0   146.3      .1       0
Bank Sta=136.3,146.3
XS Rating Curve= 0 ,0
Exp/Cntr=0.3,0.1

Type RM Length L Ch R = 1 ,5463.5  ,367.5,365.5,363.6
XS GIS Cut Line= 2
     1761194.982      175128.725     1761068.876      174993.326
#Sta/Elev= 21
     9.7 1317.57    19.5 1313.11    29.2 1308.74      39 1304.43    48.7 1299.49
    58.4  1294.6    68.2 1291.11    72.9 1291.02    77.9 1290.93    82.9 1292.39
    87.6 1293.76    97.4 1298.12   107.1 1302.52   116.9 1306.86   126.6 1311.58
   136.3 1316.55   146.1  1321.4   155.8 1325.85   165.6 1329.66   175.3 1332.52
     185 1334.37
#Mann= 3 , 0 , 0
       0      .1       0    72.9    .045       0    82.9      .1       0
Bank Sta=72.9,82.9
XS Rating Curve= 0 ,0
Exp/Cntr=0.3,0.1

Type RM Length L Ch R = 1 ,5098    ,341.6,350.1,364.9
XS GIS Cut Line= 2
     1761429.612      174841.846      1761300.85      174729.014
#Sta/Elev= 19
    10.1  1285.7    20.1 1283.14    30.2 1280.68    40.3 1278.58    50.4 1277.31
    60.4 1276.28    65.5 1275.84    70.5 1275.42    75.5 1275.43    80.6 1275.44
    90.6 1277.68   100.7 1281.38   110.8 1285.05   120.8 1288.11   130.9  1291.4
     141 1295.19   151.1 1299.24   161.1  1303.4   171.2 1307.68
#Mann= 3 , 0 , 0
       0     .06       0    65.5    .045       0    75.5     .06       0
Bank Sta=65.5,75.5
XS Rating Curve= 0 ,0
Exp/Cntr=0.3,0.1

Type RM Length L Ch R = 1 ,4747.9  ,260.9,257.5,254.2
XS GIS Cut Line= 2
     1761760.472      174834.034     1761663.569      174629.608
#Sta/Elev= 25
     9.8 1284.26    19.7 1274.84    29.5 1268.11    39.3  1265.4    49.2  1264.1
      59 1263.17    68.9 1262.52    78.7 1262.04    88.5 1261.57    98.4 1261.01
   108.2 1260.22     118 1258.96   127.9 1257.74   132.7 1257.47   137.7 1257.18
   142.7 1257.58   147.5 1257.97   157.4  1260.9   167.2 1266.03     177 1271.94
   186.9 1277.79   196.7 1283.69   206.6  1289.5   216.4 1295.24   226.2 1300.95
#Mann= 3 , 0 , 0
       0     .06       0   132.7    .045       0   142.7     .06       0
Bank Sta=132.7,142.7
XS Rating Curve= 0 ,0
Exp/Cntr=0.3,0.1

Type RM Length L Ch R = 1 ,4490.3  ,383.3,387.6,392
XS GIS Cut Line= 3
     1761970.207      174650.847     1761889.233       174535.36
      1761854.72      174508.811
#Sta/Elev= 21
    10.1 1290.07    20.1 1288.59    30.2 1285.61    40.3 1279.27    50.4 1269.54
    60.4 1257.56    70.5 1245.85    75.6 1243.01    80.6 1240.22    85.6 1240.39
    90.7 1240.55   100.7 1242.25   110.8 1244.96   120.9 1248.38     131 1251.92
     141 1255.73   149.8 1259.69   158.5 1263.87   167.2 1268.56   175.9 1273.41
   184.6 1278.67
#Mann= 3 , 0 , 0
       0     .06       0    75.6    .045       0    85.6     .06       0
Bank Sta=75.6,85.6
XS Rating Curve= 0 ,0
Exp/Cntr=0.3,0.1

Type RM Length L Ch R = 1 ,4102.7  ,171.9,168.2,164.5
XS GIS Cut Line= 3
     1762279.931      174474.258     1762227.019       174348.43
     1762174.106      174222.603
#Sta/Elev= 30
     9.8  1256.8    19.5 1252.87    29.2 1249.22      39 1245.83    48.7 1242.74
    58.5 1240.02    68.2 1237.64      78 1235.46    87.8 1233.25    97.5 1231.07
   107.3 1228.64     117 1226.46   121.8 1225.89   126.8 1225.29   131.8 1225.39
   136.5 1225.49   146.3 1226.83     156 1228.84   165.8 1230.82   175.5 1232.65
   185.3 1234.48     195 1236.32   204.8 1238.16   214.5 1239.98   224.3 1241.88
     234 1244.31   243.7 1247.99   253.5 1252.67   263.2  1257.5     273 1262.01
#Mann= 3 , 0 , 0
       0     .06       0   121.8    .045       0   131.8     .06       0
Bank Sta=121.8,131.8
XS Rating Curve= 0 ,0
Exp/Cntr=0.3,0.1

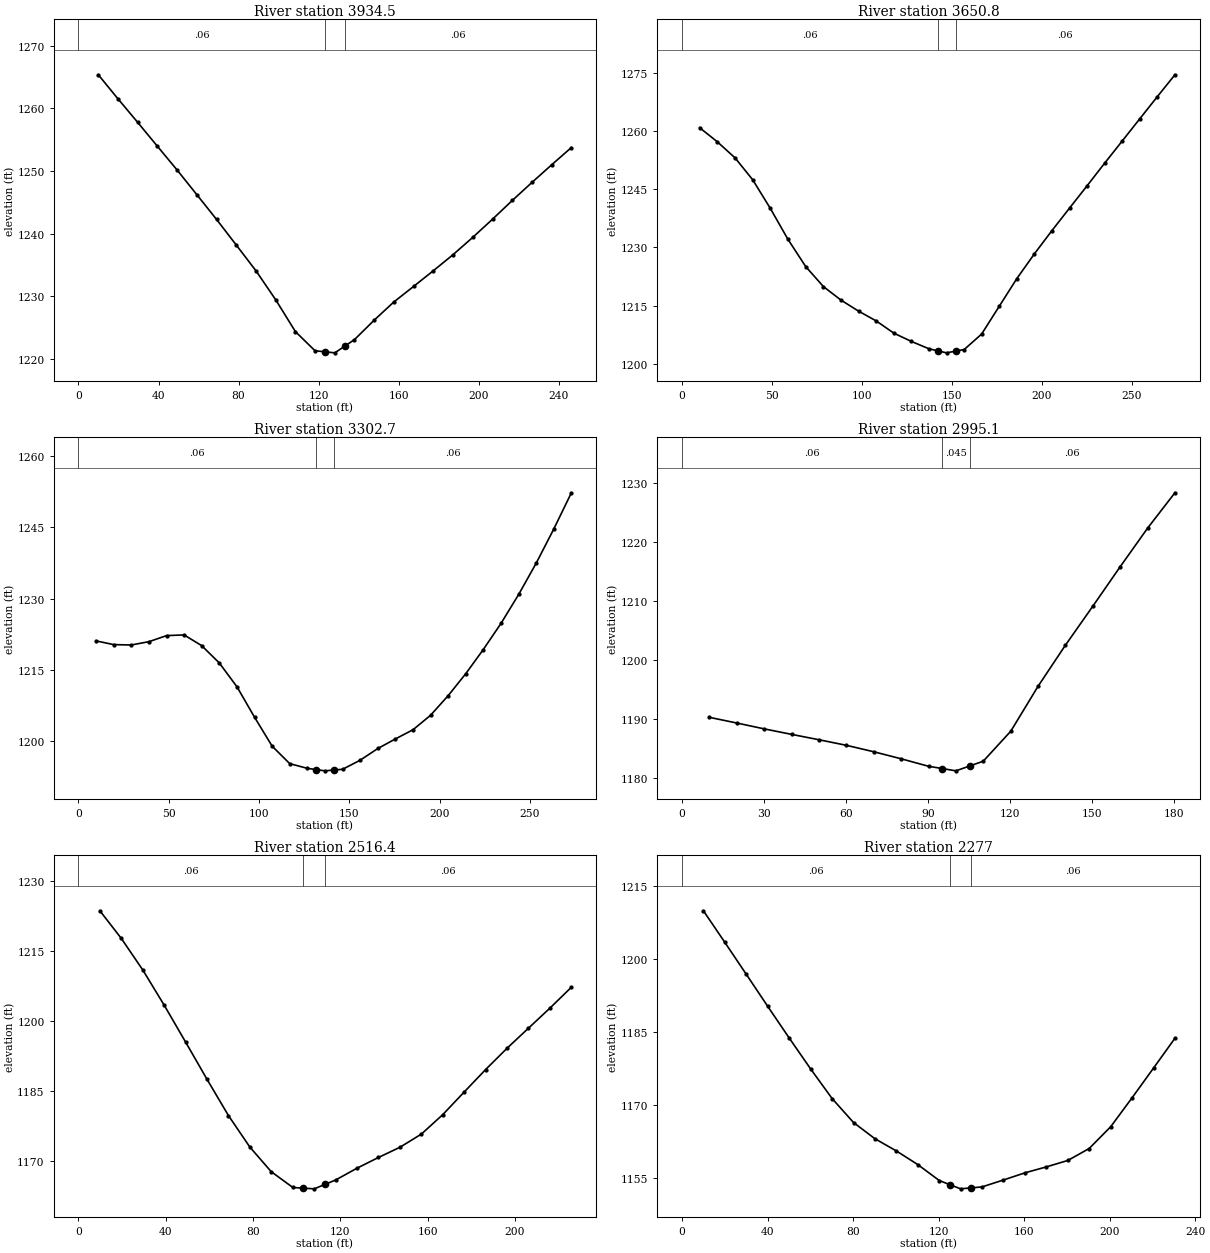
Type RM Length L Ch R = 1 ,3934.5  ,291.5,283.7,275.8
XS GIS Cut Line= 2
     1762449.413      174384.032     1762314.014      174178.278
#Sta/Elev= 27
     9.9 1265.38    19.7 1261.55    29.6 1257.77    39.4 1253.97    49.3 1250.16
    59.1 1246.24      69 1242.27    78.8  1238.2    88.7 1234.06    98.5 1229.46
   108.4 1224.35   118.2 1221.29   123.1 1221.13   128.1 1220.96   133.1 1222.04
   137.9 1223.07   147.8 1226.19   157.6 1229.09   167.5 1231.58   177.3 1234.07
   187.2 1236.65     197  1239.4   206.9 1242.31   216.8 1245.31   226.6 1248.18
   236.5 1251.01   246.3 1253.76
#Mann= 3 , 0 , 0
       0     .06       0   123.1    .045       0   133.1     .06       0
Bank Sta=123.1,133.1
XS Rating Curve= 0 ,0
Exp/Cntr=0.3,0.1

Type RM Length L Ch R = 1 ,3650.8  ,351.2,348.1,345.1
XS GIS Cut Line= 3
     1762673.935      174229.749     1762631.273      174130.491
     1762494.546      174036.242
#Sta/Elev= 30
     9.8 1260.84    19.6 1257.22    29.5 1253.06    39.3 1247.42    49.1 1240.05
    58.9 1232.08    68.8 1225.05    78.6 1219.91    88.4 1216.42    98.2 1213.57
     108 1211.05   117.8  1207.9   127.6 1205.76   137.3 1203.88   142.1 1203.36
   147.1 1202.83   152.1 1203.26   156.9 1203.68   166.6 1207.66   176.4 1214.82
   186.2 1221.97     196 1228.37   205.7 1234.32   215.5 1240.13   225.3  1245.9
     235 1251.69   244.8 1257.42   254.6 1263.16   264.3 1268.83   274.1 1274.48
#Mann= 3 , 0 , 0
       0     .06       0   142.1    .045       0   152.1     .06       0
Bank Sta=142.1,152.1
XS Rating Curve= 0 ,0
Exp/Cntr=0.3,0.1

Type RM Length L Ch R = 1 ,3302.7  ,305.6,307.6,309.5
XS GIS Cut Line= 3
     1762910.617      173877.841     1762787.793      173818.289
     1762664.968      173758.738
#Sta/Elev= 30
     9.8 1221.06    19.5 1220.28    29.2  1220.2      39  1220.9    48.8 1222.18
    58.5 1222.32    68.2 1220.07      78 1216.41    87.8 1211.37    97.5 1204.98
   107.3 1198.85     117 1195.19   126.7  1194.2   131.5 1193.94   136.5 1193.67
   141.5 1193.84   146.3    1194     156 1195.91   165.8 1198.38   175.5 1200.39
   185.3 1202.34     195 1205.38   204.8 1209.54   214.5 1214.15   224.2 1219.24
     234 1224.74   243.8 1230.85   253.5 1237.44   263.2 1244.61     273 1252.29
#Mann= 3 , 0 , 0
       0     .06       0   131.5    .045       0   141.5     .06       0
Bank Sta=131.5,141.5
XS Rating Curve= 0 ,0
Exp/Cntr=0.3,0.1

Type RM Length L Ch R = 1 ,2995.1  ,479.7,478.7,477.8
XS GIS Cut Line= 2
     1763027.604      173605.173     1762873.621      173510.924
#Sta/Elev= 20
      10 1190.25    20.1 1189.28    30.1 1188.29    40.1 1187.36    50.1 1186.45
    60.2  1185.5    70.2 1184.41    80.2 1183.22    90.3 1181.94    95.3 1181.56
   100.3 1181.17   105.3 1181.99   110.3  1182.8   120.4  1187.9   130.4 1195.53
   140.4 1202.49   150.4 1209.08   160.5 1215.83   170.5 1222.35   180.5 1228.35
#Mann= 3 , 0 , 0
       0     .06       0    95.3    .045       0   105.3     .06       0
Bank Sta=95.3,105.3
XS Rating Curve= 0 ,0
Exp/Cntr=0.3,0.1

Type RM Length L Ch R = 1 ,2516.4  ,236,239.4,242.7
XS GIS Cut Line= 2
     1763368.002      173291.548     1763170.213      173182.698
#Sta/Elev= 25
     9.8 1223.62    19.6 1217.71    29.4 1210.99    39.3 1203.39    49.1  1195.5
    58.9 1187.54    68.7  1179.8    78.5 1173.06    88.3 1167.79    98.2 1164.41
     103 1164.27     108 1164.12     113 1165.09   117.8 1166.01   127.6 1168.54
   137.4 1170.83   147.2    1173   157.1 1175.84   166.9 1180.01   176.7 1184.84
   186.5 1189.64   196.3 1194.19   206.1 1198.48   215.9 1202.76   225.8 1207.26
#Mann= 3 , 0 , 0
       0     .06       0     103    .045       0     113     .06       0
Bank Sta=103,113
XS Rating Curve= 0 ,0
Exp/Cntr=0.3,0.1

Type RM Length L Ch R = 1 ,2277    ,482.7,482.5,482.4
XS GIS Cut Line= 2
     1763468.887      173108.362     1763288.355      172964.998
#Sta/Elev= 25
      10 1209.94      20 1203.45    30.1 1196.83    40.1 1190.25    50.1 1183.76
    60.1 1177.41    70.2 1171.28    80.2 1166.35    90.2 1163.02   100.2 1160.51
   110.3 1157.68   120.3 1154.41   125.3 1153.55   130.3  1152.7   135.3  1152.9
   140.3  1153.1   150.3 1154.52   160.4    1156   170.4 1157.22   180.4 1158.54
   190.4    1161   200.5  1165.5   210.5 1171.46   220.5 1177.56   230.5 1183.69
#Mann= 3 , 0 , 0
       0     .06       0   125.3    .045       0   135.3     .06       0
Bank Sta=125.3,135.3
XS Rating Curve= 0 ,0
Exp/Cntr=0.3,0.1

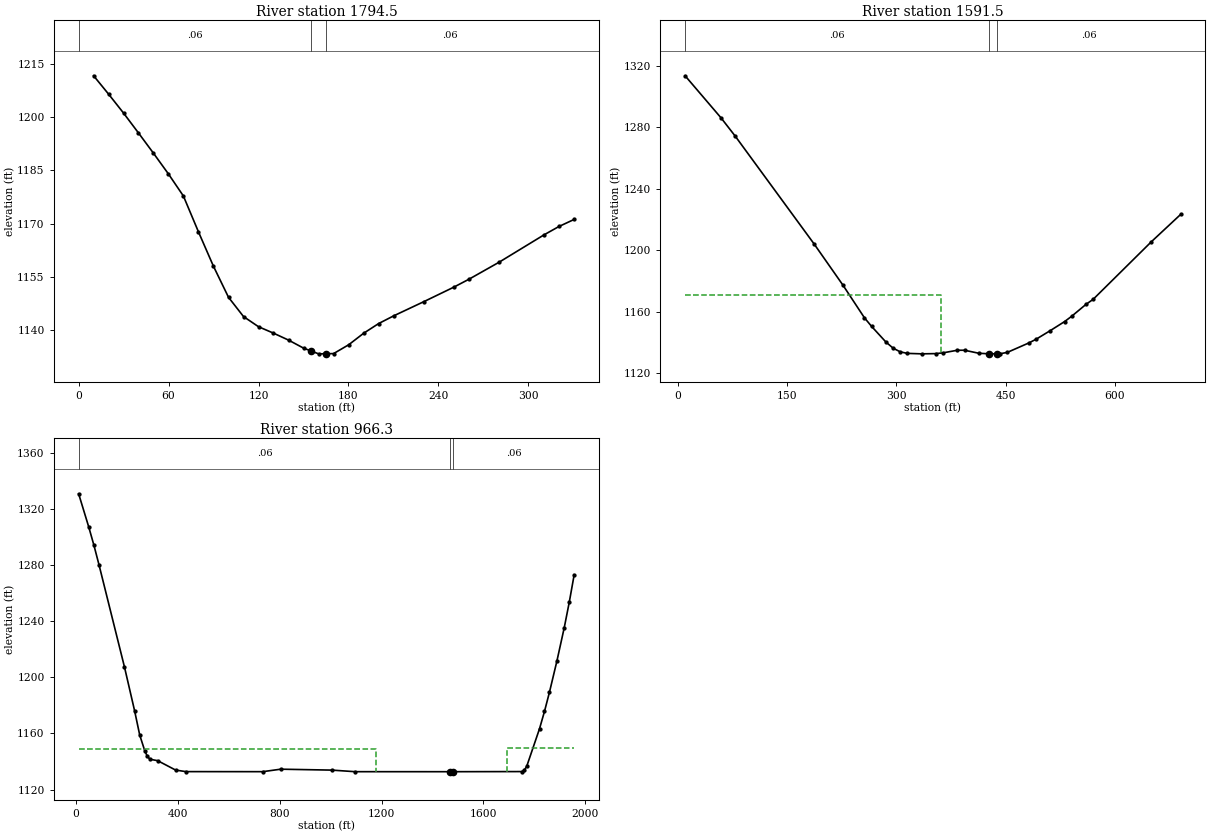
Type RM Length L Ch R = 1 ,1794.5  ,200.3,203,205.7
XS GIS Cut Line= 3
     1763785.935      172833.798     1763790.983      172764.089
     1763586.812      172602.048
#Sta/Elev= 30
      10 1211.64      20 1206.47      30 1201.13    39.9 1195.57    49.9 1189.87
    59.9 1184.03    69.9 1177.81    79.9 1167.77    89.9  1158.1     100 1149.31
     110  1143.9     120 1141.04     130 1139.23   140.1 1137.26   150.1 1135.01
   155.1 1134.21   160.1 1133.41   165.1 1133.44   170.1 1133.48   180.2 1135.97
   190.2 1139.22   200.2 1141.94   210.2  1144.1   230.3 1148.09   250.3 1152.17
   260.4  1154.4   280.4 1159.16   310.5 1166.89   320.5 1169.25   330.6 1171.23
#Mann= 3 , 0 , 0
       0     .06       0   155.1    .045       0   165.1     .06       0
Bank Sta=155.1,165.1
XS Rating Curve= 0 ,0
Exp/Cntr=0.3,0.1

Type RM Length L Ch R = 1 ,1591.5  ,618.8,625.2,631.5
XS GIS Cut Line= 4
     1763917.741      172893.781     1763911.259      172637.756
     1763690.883      172414.139     1763570.973      172407.658
#Sta/Elev= 30
     9.9 1313.46    59.1 1286.18    78.8 1274.17   187.2 1204.01   226.6 1177.36
   256.1 1156.14   265.9 1150.56   285.5 1140.42   295.4 1136.42   305.2 1134.01
     315    1133   334.6  1132.7   354.2 1132.85     364 1133.35   383.7 1135.04
   393.5 1135.04   413.1 1133.08   427.7 1132.71   437.7 1132.74   442.5 1132.78
   452.3 1133.65   481.8 1139.78   491.6 1142.15   511.2 1147.78   530.8 1153.65
   540.6 1157.12   560.3 1164.88   570.1 1168.14   650.1 1205.61   690.2 1223.32
#Mann= 3 , 0 , 0
     9.9     .06       0   427.7    .045       0   437.7     .06       0
#XS Ineff= 2 , 0
          361.74 1171.03
Permanent Ineff=
       F       F
Bank Sta=427.7,437.7
XS Rating Curve= 0 ,0
Exp/Cntr=0.3,0.1

Type RM Length L Ch R = 1 ,966.3   ,944.2,966.3,988.5
XS GIS Cut Line= 4
     1764554.723      173267.639     1764569.698      173018.041
     1763801.137      171648.517     1763665.871      171633.204
#Sta/Elev= 30
      10 1330.83      50    1307      70 1294.17      90 1280.21     190  1207.4
     230 1176.01     250 1158.79   270.2 1147.38   280.2 1143.58   290.3 1141.56
   320.5 1140.56     391 1133.86   431.3 1132.76   733.3 1132.72   803.7 1134.49
  1005.1 1133.83  1095.7 1132.71    1470  1132.7  1475.4  1132.6    1480  1132.7
    1750 1132.79  1760.1 1133.58  1770.2 1136.53  1820.5 1163.34  1839.9 1175.63
  1859.4 1189.28  1888.6 1211.46  1917.7 1235.47  1937.2 1253.41  1956.6 1273.08
#Mann= 3 , 0 , 0
      10     .06       0    1470    .045       0    1480     .06       0
#XS Ineff= 2 , 0
         1177.85 1148.89 1691.28         1149.82
Permanent Ineff=
       F       F
Bank Sta=1470,1480
XS Rating Curve= 0 ,0
Exp/Cntr=0.3,0.1

Chan Stop Cuts=-1
Use User Specified Reach Order=0